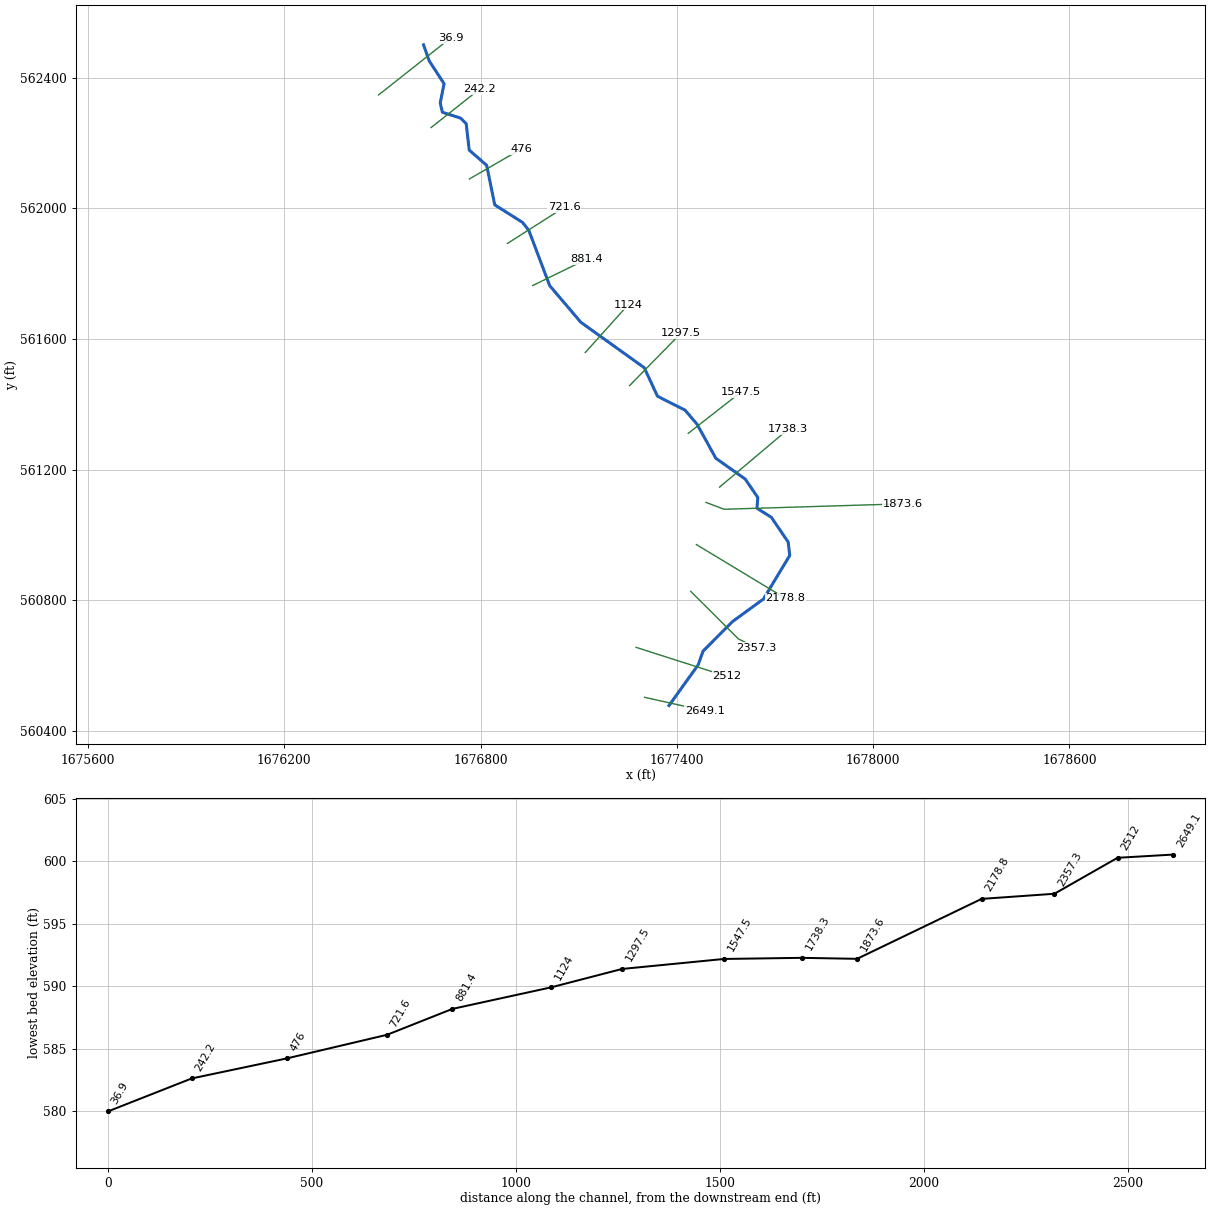
--- NP9.prj (project) ---

Proj Title=NP9
Current Plan=p01
Default Exp/Contr=0,0
English Units
Geom File=g01
Flow File=f01
Plan File=p01
BEGIN DESCRIPTION:
AMEC Environment & Infrastructure, 2013
Projection: NAD 1983 State Plane West Virginia South FIPS 4702 (US Feet)
Vertical Datum: NAVD 1988
END DESCRIPTION:
DSS Export Rating Curves= 0
DSS Export Rating Curve Sorted= 0
DSS Export Volume Flow Curves= 0
DXF OffsetX= 0
DXF OffsetY= 0
DXF ScaleX= 0
DXF ScaleY= 0

--- NP9.p01 (plan) ---

Plan Title=Floodplain
Program Version=4.00
Geom File=g01
Flow File=f01
K Sum by GR=0
Std Step Tol=0.01
Critical Tol=0.01
Num of Std Step Trials=20
Max Error Tol=0.3
Flow Tol Ratio=0.001
Split Flow NTrial=30
Split Flow Tol=0.02
Split Flow Ratio=0.02
Log Output Level=0
Friction Slope Method=1
Unsteady Friction Slope Method=2
Unsteady Bridges Friction Slope Method=1
Global Log Level=0
CheckData=False
Run HTab=0
Run UNet=0
Run PostProcess=0
UNET Theta=0
UNET Theta Warmup=0
UNET ZTol=0
UNET ZSATol=0
UNET MxIter=0
UNET MaxInSteps=0
UNET DtIC=0
UNET DtMin=0
UNET MaxCRTS=0
UNET WFStab=0
UNET SFStab=0
UNET WFX=0
UNET SFX=0
UNET DSS MLevel=0
UNET DZMax Abort=0
UNET Convert EG Bridges=0
UNET Use Existing IB Tables=0
UNET Froude Limit=0
UNET Froude Power=0
Write IC File=0
Echo Input=False
Echo Output=False
Write Detailed=0

--- NP9.f01 (steady flow) ---

Flow Title=USGS Regress. Eqn. (2010) - Western-Plateaus
Program Version=4.10
Number of Profiles= 1
Profile Names=P100yr
River Rch & RM=NP9,Main            ,2649.1
     888
River Rch & RM=NP9,Main            ,881.4
     898
River Rch & RM=NP9,Main            ,242.2
     919
Boundary for River Rch & Prof#=NP9,Main            , 1
Up Type= 0
Dn Type= 3
Dn Slope=0.01234
DSS Import GetInterval= 0
DSS Import GetPeak= 0
DSS Import FillOption= 0

--- NP9.g01 (geometry) ---

Geom Title=USGS 3m DEM
Program Version=4.10

River Reach=NP9             ,Main
Reach XY= 30
     1677376.095      560477.523     1677465.082      560601.694
     1677480.273       560644.24     1677570.131      560734.548
     1677664.767      560803.584     1677745.185      560937.113
       1677740.3      560978.316     1677688.899       561053.83
     1677644.903      561081.776     1677647.504      561114.645
     1677609.123      561171.031     1677519.222       561234.69
     1677461.931      561338.857     1677425.472      561381.826
     1677340.837      561424.794     1677300.472      561512.034
     1677106.462      561651.357      1677011.41      561763.336
     1676947.608      561932.607     1676928.077      561957.347
     1676843.441      562010.732     1676818.702      562131.826
     1676765.316      562178.701     1676756.202       562259.43
     1676739.275      562276.357     1676683.285      562294.586
     1676676.775      562323.232     1676688.493      562381.826
      1676642.92      562452.138     1676625.743      562500.911

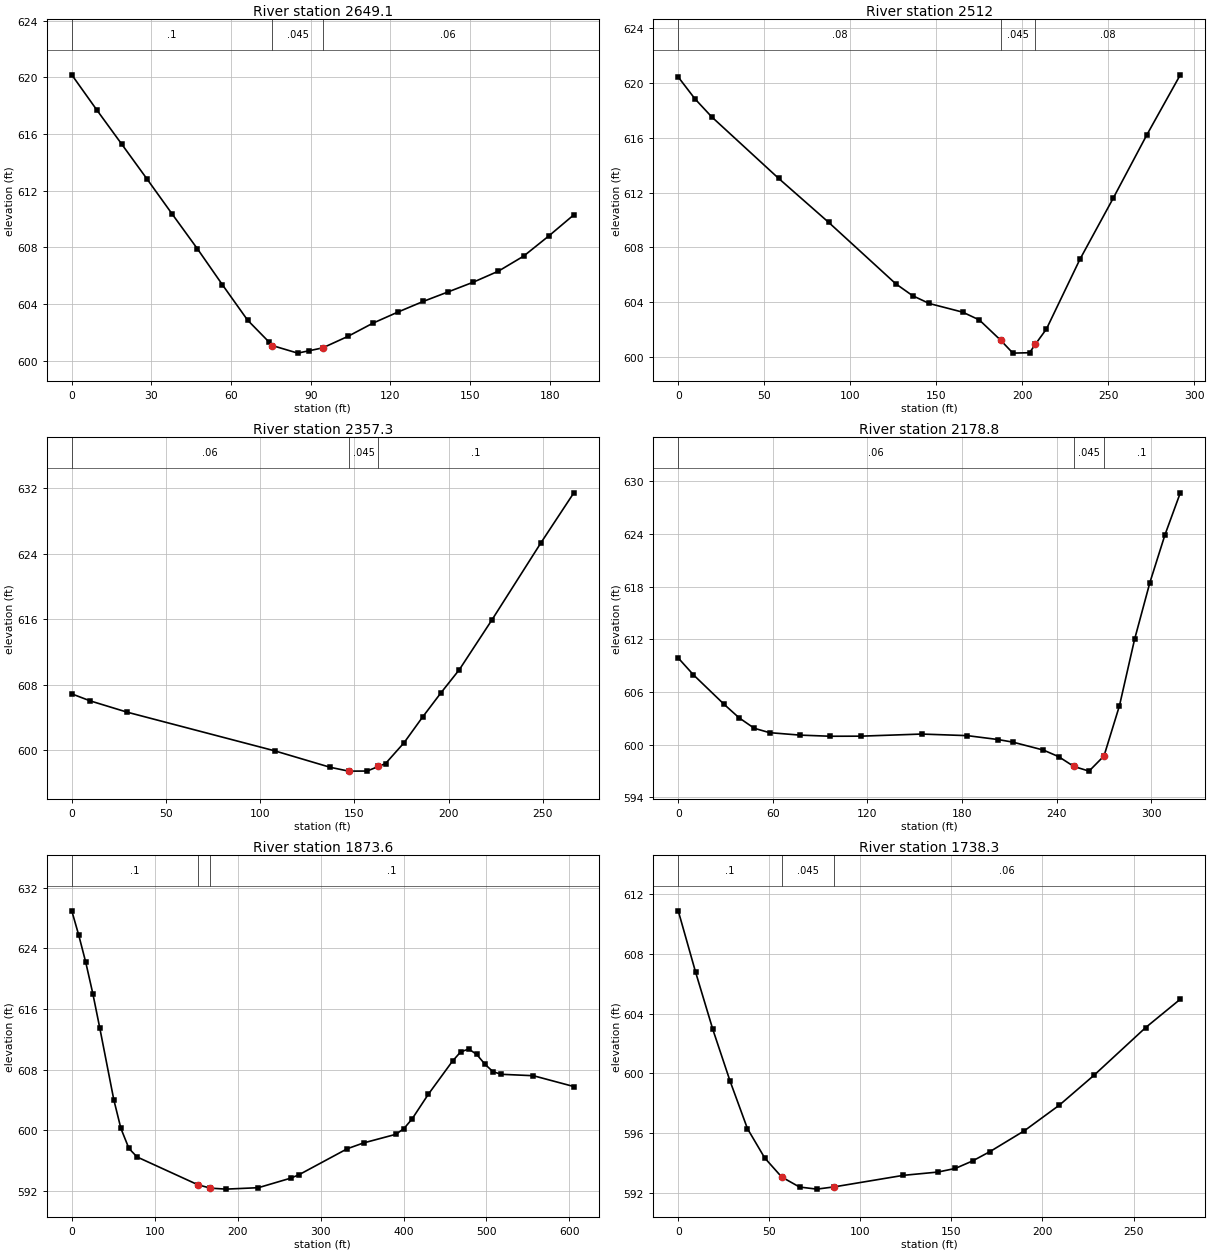
Type RM Length L Ch R = 1 ,2649.1  ,139.4,137.1,134.7
XS GIS Cut Line= 2
     1677301.512      560502.561     1677486.023      560461.334
#Sta/Elev= 23
       0  620.17     9.4   617.7    18.9  615.26    28.4  612.81    37.8  610.36
    47.3  607.91    56.7  605.38    66.2  602.88    74.2  601.35    75.6  601.08
    85.1  600.55    89.2  600.71    94.5  600.92     104  601.73   113.4  602.66
   122.9  603.45   132.3  604.19   141.8  604.87   151.2  605.55   160.7  606.33
   170.2  607.39   179.6   608.8   189.1   610.3
#Mann= 3 , 0 , 0
       0      .1       0    75.6    .045       0    94.5     .06       0
Bank Sta=75.6,94.5
XS Rating Curve= 0 ,0
Exp/Cntr=0.3,0.1

Type RM Length L Ch R = 1 ,2512    ,165.7,154.7,143.6
XS GIS Cut Line= 2
     1677275.451      560655.591     1677553.305      560566.618
#Sta/Elev= 19
       0  620.43     9.7  618.84    19.4  617.53    58.4  613.03    87.5  609.82
   126.4  605.35   136.2  604.48   145.9  603.91   165.3  603.28     175  602.71
   187.4  601.23   194.5  600.29   204.2  600.32  207.46  600.92     214  602.05
   233.4  607.12   252.8  611.59   272.3   616.2   291.8  620.59
#Mann= 3 , 0 , 0
       0     .08       0   187.4    .045       0  207.46     .08       0
Bank Sta=187.4,207.46
XS Rating Curve= 0 ,0
Exp/Cntr=0.3,0.1

Type RM Length L Ch R = 1 ,2357.3  ,172.9,178.5,184
XS GIS Cut Line= 3
     1677442.578      560827.089     1677588.026      560681.666
     1677642.295      560654.538
#Sta/Elev= 16
       0  606.86     9.8     606    29.4  604.62   107.7  599.89   137.1  597.88
   146.9  597.41   156.7  597.42   162.7  597.98   166.5  598.34   176.3  600.88
   186.1  604.01   195.9  606.99   205.7  609.84     223  615.93     249  625.36
   266.4  631.45
#Mann= 3 , 0 , 0
       0     .06       0   146.9    .045       0   162.7      .1       0
Bank Sta=146.9,162.7
XS Rating Curve= 0 ,0
Exp/Cntr=0.3,0.1

Type RM Length L Ch R = 1 ,2178.8  ,292.5,305.2,314.6
XS GIS Cut Line= 2
     1677459.931      560970.355     1677732.365      560805.407
#Sta/Elev= 23
       0  609.88     9.6  607.97      29  604.62    38.6  603.07    48.2  601.88
    57.9  601.38    77.2   601.1    96.5  600.97   115.8  600.98   154.4  601.22
   183.4  601.04   202.7   600.6   212.3   600.3   231.6   599.4   241.3  598.65
   250.9  597.54   260.6     597   270.1  598.73   279.9  604.45   289.5  612.01
   299.2  618.47   308.8  623.92   318.5  628.68
#Mann= 3 , 0 , 0
       0     .06       0   250.9    .045       0   270.1      .1       0
Bank Sta=250.9,270.1
XS Rating Curve= 0 ,0
Exp/Cntr=0.3,0.1

Type RM Length L Ch R = 1 ,1873.6  ,119.7,135.3,154.2
XS GIS Cut Line= 3
     1677489.224      561099.513      1677544.55       561078.55
     1678090.502      561095.224
#Sta/Elev= 30
       0  628.96     8.4  625.75    16.9  622.14    25.4  618.02    33.8  613.47
    50.7     604    59.2  600.23    68.9  597.58    78.7  596.45   152.2  592.77
   167.2  592.33     186   592.2     225  592.39     264  593.65   273.8  594.09
   332.3  597.54   351.8   598.3   390.8  599.44   400.5   600.2   410.3  601.46
   429.8  604.71   459.1  609.11   468.8  610.31   478.6  610.71   488.3  609.99
   498.1  608.71   507.8  607.72   517.6  607.37   556.6  607.18   605.4  605.75
#Mann= 3 , 0 , 0
       0      .1       0   152.2    .045       0   167.2      .1       0
Bank Sta=152.2,167.2
XS Rating Curve= 0 ,0
Exp/Cntr=0.3,0.1

Type RM Length L Ch R = 1 ,1738.3  ,191.3,190.8,190.2
XS GIS Cut Line= 2
     1677530.463      561146.186     1677741.003        561324.2
#Sta/Elev= 20
       0  610.86     9.5  606.78      19  602.94    28.5  599.48      38  596.32
    47.5  594.36    56.8  593.09    66.6  592.42    76.1  592.28    85.6  592.43
   123.6   593.2   142.6  593.42   152.1  593.66   161.6  594.16   171.1  594.78
   190.1  596.18   209.2  597.88   228.2  599.87   256.7  603.07   275.7  604.96
#Mann= 3 , 0 , 0
       0      .1       0    56.8    .045       0    85.6     .06       0
Bank Sta=56.8,85.6
XS Rating Curve= 0 ,0
Exp/Cntr=0.3,0.1

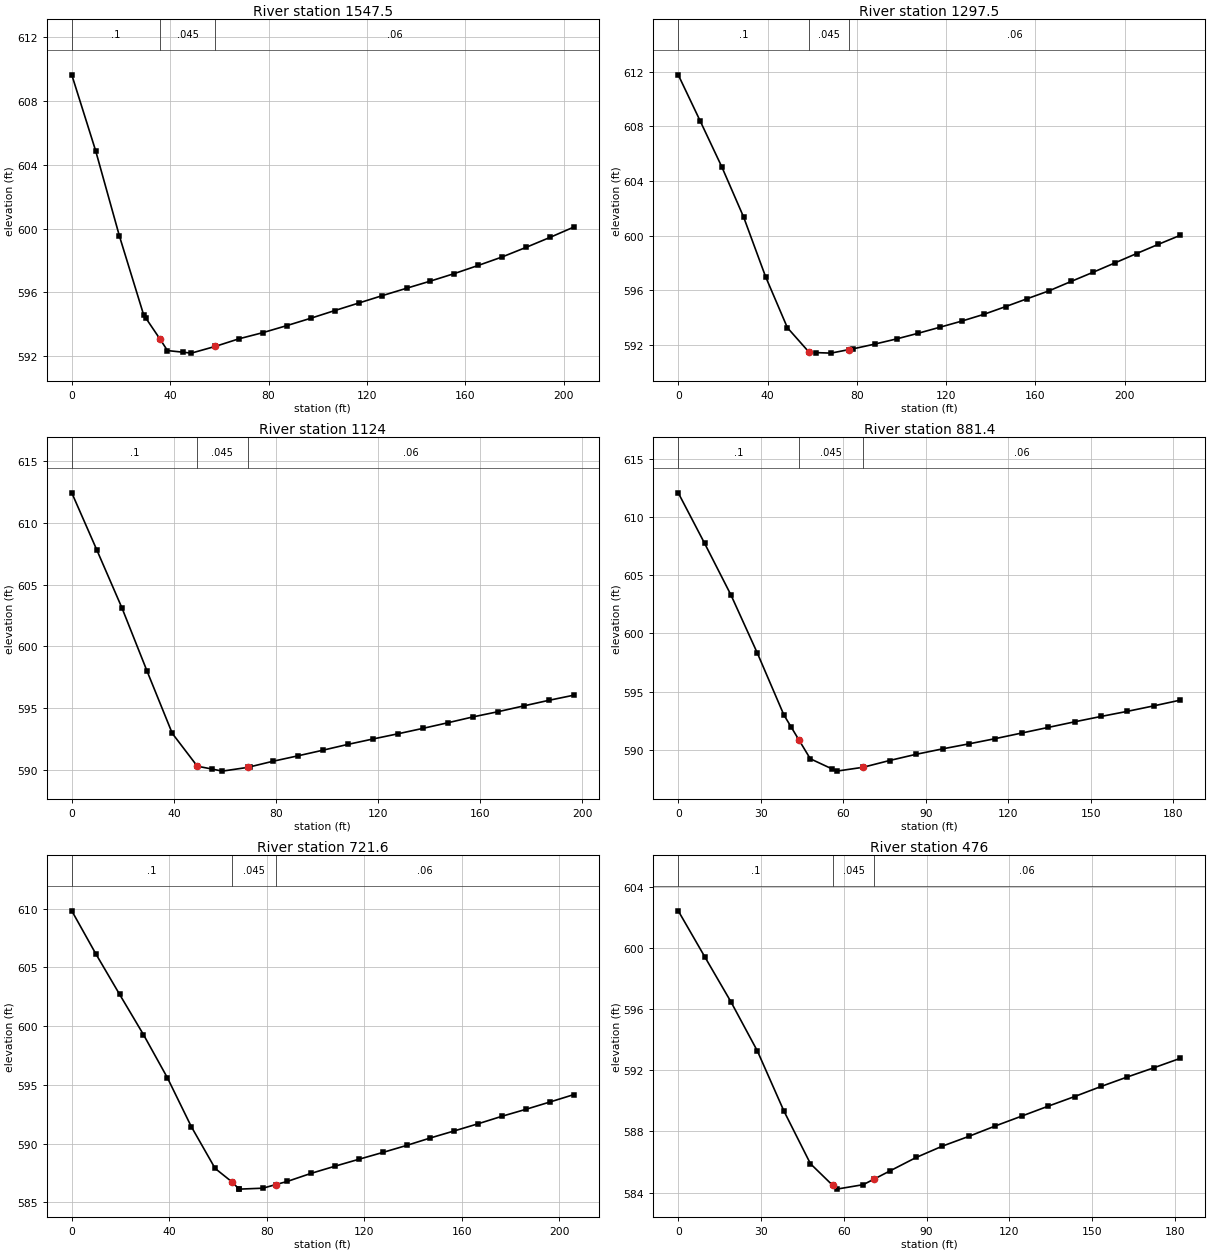
Type RM Length L Ch R = 1 ,1547.5  ,247.4,250,252.5
XS GIS Cut Line= 2
     1677434.939      561311.149     1677595.558      561437.063
#Sta/Elev= 25
       0  609.65     9.7  604.89    19.4  599.52    29.2   594.6    30.1  594.39
   35.92  593.06    38.9  592.35    45.1  592.25    48.6  592.19    58.3  592.61
      68  593.09    77.8  593.48    87.5  593.92    97.2  594.38   106.9  594.86
   116.6  595.33   126.3   595.8   136.1  596.26   145.8  596.71   155.5  597.18
   165.2  597.69   174.9  598.22   184.6  598.82   194.4  599.45   204.1   600.1
#Mann= 3 , 0 , 0
       0      .1       0   35.92    .045       0    58.3     .06       0
Bank Sta=35.92,58.3
XS Rating Curve= 0 ,0
Exp/Cntr=0.3,0.1

Type RM Length L Ch R = 1 ,1297.5  ,172.5,173.5,174.4
XS GIS Cut Line= 2
     1677255.846      561457.655     1677413.206      561618.298
#Sta/Elev= 26
       0  611.77     9.8   608.4    19.6     605    29.3  601.35    39.1     597
    48.9  593.25    58.7  591.44    61.5  591.43    68.4  591.39    76.5  591.65
    78.2   591.7      88  592.05    97.8  592.43   107.6  592.85   117.3  593.29
   127.1  593.74   136.9  594.23   146.7   594.8   156.4  595.38   166.2  595.96
     176  596.64   185.8  597.31   195.5  597.99   205.3  598.68   215.1  599.36
   224.9  600.02
#Mann= 3 , 0 , 0
       0      .1       0    58.7    .045       0    76.5     .06       0
Bank Sta=58.7,76.5
XS Rating Curve= 0 ,0
Exp/Cntr=0.3,0.1

Type RM Length L Ch R = 1 ,1124    ,251.2,242.6,234
XS GIS Cut Line= 2
      1677120.17      561558.579     1677251.483      561705.111
#Sta/Elev= 23
       0  612.42     9.8  607.81    19.7   603.1    29.5  598.01    39.4  592.97
    49.2  590.32    54.9  590.09      59  589.92    68.9  590.22    69.9  590.27
    78.7  590.71    88.5  591.15    98.4  591.61   108.2  592.08   118.1  592.52
   127.9  592.94   137.7  593.38   147.6  593.84   157.4  594.31   167.2  594.73
   177.1  595.19   186.9  595.64   196.8  596.06
#Mann= 3 , 0 , 0
       0      .1       0    49.2    .045       0    68.9     .06       0
Bank Sta=49.2,68.9
XS Rating Curve= 0 ,0
Exp/Cntr=0.3,0.1

Type RM Length L Ch R = 1 ,881.4   ,157.1,159.8,162.4
XS GIS Cut Line= 2
     1676959.522      561763.694     1677123.401      561844.024
#Sta/Elev= 23
       0  612.06     9.6  607.72    19.2  603.28    28.8  598.29    38.4  593.01
      41  591.99   43.94590.8392      48  589.25      56  588.37    57.6  588.19
    67.2  588.52    76.8   589.1    86.4  589.63    96.1   590.1   105.7  590.53
   115.3  590.98   124.9  591.46   134.5  591.94   144.1  592.42   153.7  592.88
   163.3  593.32   172.9  593.79   182.5  594.28
#Mann= 3 , 0 , 0
       0      .1       0   43.94    .045       0    67.2     .06       0
Bank Sta=43.94,67.2
XS Rating Curve= 0 ,0
Exp/Cntr=0.3,0.1

Type RM Length L Ch R = 1 ,721.6   ,246.5,245.5,244.4
XS GIS Cut Line= 2
     1676882.451      561892.843     1677056.096      562003.562
#Sta/Elev= 25
       0  609.82     9.8  606.18    19.6  602.71    29.4  599.28    39.2  595.61
      49  591.45    58.8  587.88   65.85  586.71    68.6  586.12    68.7  586.12
    78.4   586.2    83.7  586.51    88.3  586.77    98.1  587.46   107.9  588.07
   117.7  588.66   127.5  589.24   137.3  589.84   147.1  590.48   156.9  591.08
   166.7  591.69   176.5  592.33   186.3  592.92   196.1  593.54   205.9  594.17
#Mann= 3 , 0 , 0
       0      .1       0   65.85    .045       0    83.7     .06       0
Bank Sta=65.85,83.7
XS Rating Curve= 0 ,0
Exp/Cntr=0.3,0.1

Type RM Length L Ch R = 1 ,476     ,230,233.8,236.4
XS GIS Cut Line= 2
     1676766.303      562090.364     1676923.669      562181.546
#Sta/Elev= 22
       0  602.42     9.6  599.42    19.1  596.47    28.7  593.25    38.3  589.33
    47.9  585.89      56  584.47    57.4  584.23      67  584.52      71  584.89
    76.6  585.41    86.2   586.3    95.7  587.04   105.3  587.68   114.9  588.36
   124.4     589     134  589.65   143.6  590.28   153.2  590.94   162.7  591.56
   172.3  592.16   181.9  592.78
#Mann= 3 , 0 , 0
       0      .1       0      56    .045       0      71     .06       0
Bank Sta=56,71
XS Rating Curve= 0 ,0
Exp/Cntr=0.3,0.1

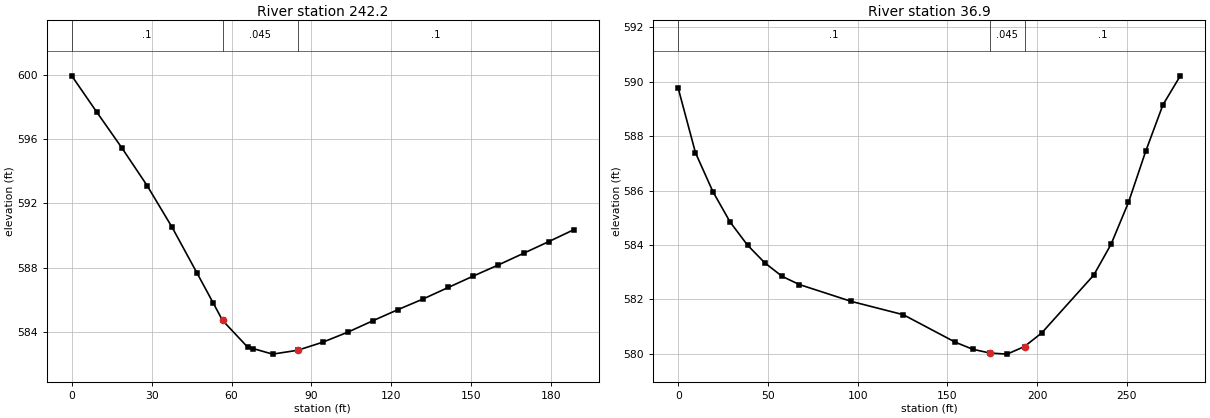
Type RM Length L Ch R = 1 ,242.2   ,205.3,205.3,206.3
XS GIS Cut Line= 2
     1676649.073      562247.728     1676796.669      562364.957
#Sta/Elev= 23
       0  599.93     9.4  597.67    18.8  595.45    28.3   593.1    37.7   590.5
    47.1  587.64    53.2  585.77    56.6  584.72      66  583.06    68.2  582.96
    75.4  582.62    84.8  582.86    94.2  583.36   103.7  583.99   113.1   584.7
   122.5  585.39   131.9  586.05   141.4  586.77   150.8  587.48   160.2  588.17
   169.6  588.89   179.1  589.62   188.5  590.36
#Mann= 3 , 0 , 0
       0      .1       0    56.6    .045       0    84.8      .1       0
Bank Sta=56.6,84.8
XS Rating Curve= 0 ,0
Exp/Cntr=0.3,0.1

Type RM Length L Ch R = 1 ,36.9    ,44.7,36.9,29.2
XS GIS Cut Line= 2
     1676488.434      562347.565     1676707.657      562521.238
#Sta/Elev= 22
       0  589.76     9.6  587.39    19.3  585.96    28.9  584.84    38.6  583.99
    48.2  583.34    57.9  582.84    67.5  582.54    96.4  581.92   125.4  581.43
   154.3  580.42     164  580.16   173.6  580.02   183.2  579.98   192.9  580.26
   202.5  580.76   231.5  582.89   241.1  584.02   250.8  585.56   260.4  587.44
     270  589.15   279.7  590.22
#Mann= 3 , 0 , 0
       0      .1       0   173.6    .045       0   192.9      .1       0
Bank Sta=173.6,192.9
XS Rating Curve= 0 ,0
Exp/Cntr=0.3,0.1

Chan Stop Cuts=-1
Use User Specified Reach Order=0
Composite Channel Slope=5